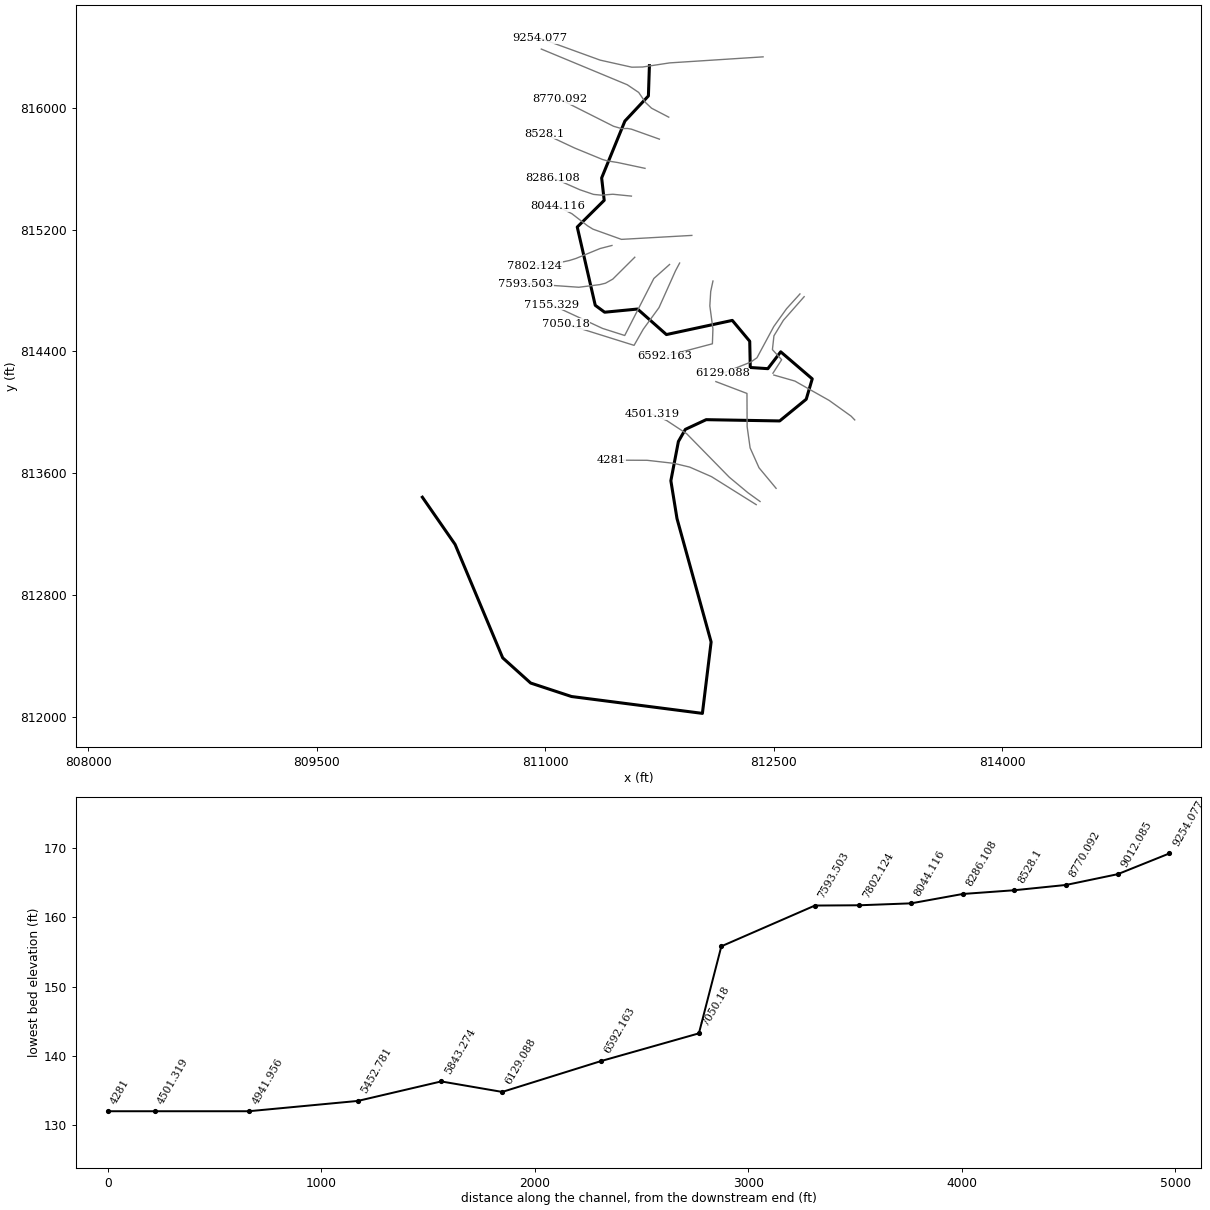
--- 18130_ras.prj (project) ---

Proj Title=18130
Current Plan=p01
Default Exp/Contr=0.3,0.1
English Units
Geom File=g01
Flow File=f01
Plan File=p01
Y Axis Title=Elevation
X Axis Title(PF)=Main Channel Distance
X Axis Title(XS)=Station
BEGIN DESCRIPTION:
RFD model 18130 exported to HEC-RAS
END DESCRIPTION:

--- 18130_ras.p01 (plan) ---

Plan Title=Plan 01
Program Version=4.10
Short Identifier=Plan 01
Geom File=g01
Flow File=f01
Subcritical Flow
Calc Critical at every XS
Secant Critical Depth

--- 18130_ras.f01 (steady flow) ---

Flow Title=Flow 01
Program Version=5.01
Number of Profiles= 6
Profile Names=10yr,25yr,50yr,100yr,100plus,500yr
River Rch & RM=18130,17,9254.077
  935.25 1533.09 2105.75 2639.01 3852.96 5365.36
River Rch & RM=18130,17,9012.085
  938.96 1539.52  2114.9 2650.83 3870.21 5387.55
River Rch & RM=18130,17,8770.092
  941.35 1543.66  2120.8 2658.45 3881.34 5401.89
River Rch & RM=18130,17,  8528.1
   975.6 1603.25 2205.81 2768.48 4041.99  5608.8
River Rch & RM=18130,17,8286.108
  978.13 1607.66 2212.12 2776.66 4053.92  5624.2
River Rch & RM=18130,17,8044.116
 1111.45 1835.98 2534.84 3191.01 4658.87 6378.13
River Rch & RM=18130,17,7802.124
 1114.06 1840.55 2541.41 3199.55 4671.34 6393.99
River Rch & RM=18130,17,7593.503
 1116.48 1844.78 2547.48 3207.43 4682.85 6408.61
River Rch & RM=18130,17,7155.329
  1119.7 1850.44 2555.58 3217.96 4698.21 6428.09
River Rch & RM=18130,17, 7050.18
 1129.56  1867.7 2580.32 3250.11 4745.16 6487.61
River Rch & RM=18130,17,6592.163
 1140.08 1886.08 2606.64 3284.26 4795.02 6550.54
River Rch & RM=18130,17,6129.088
 1149.37 1902.32 2629.87 3314.41 4839.04    6606
River Rch & RM=18130,17,5843.274
 1150.38 1904.08 2632.39 3317.69 4843.82 6612.02
River Rch & RM=18130,17,5452.781
 1172.35 1942.23  2686.8 3388.08  4946.6  6740.3
River Rch & RM=18130,17,4941.956
 1172.74 1942.92 2687.79 3389.38 4948.49 6742.69
River Rch & RM=18130,17,4501.319
  1133.2 1874.07 2589.44 3261.94 4762.43 6509.42
Boundary for River Rch & Prof#=18130,17,1
Up Type= 0
Dn Type= 2
Boundary for River Rch & Prof#=18130,17,2
Up Type= 0
Dn Type= 2
Boundary for River Rch & Prof#=18130,17,2
Up Type= 0
Dn Type= 2
Boundary for River Rch & Prof#=18130,17,2
Up Type= 0
Dn Type= 2
Boundary for River Rch & Prof#=18130,17,2
Up Type= 0
Dn Type= 2
Boundary for River Rch & Prof#=18130,17,2
Up Type= 0
Dn Type= 2

--- 18130_ras.g01 (geometry) ---

Geom Title=18130
Program Version=4.10

River Reach=18130,17
Reach XY= 30
811683.267859697816275.847976193811676.638883084816077.195869908
811522.254403472815912.115865409811369.700550735815538.815678611
811386.394253999815391.803125635811209.506802469815216.400838658
811327.630421489814702.444667593811389.341687977814657.158206925
811605.362861454 814677.99273634 811794.90667966814510.418129951
812227.518375546814603.398836777812341.876479119814466.573757917
812345.536932826814294.198773384812460.890294343814286.519984618
812545.317081541814397.167116553812752.358533561814219.633089155
812712.882583141814085.853479236812538.530468494813943.301435798
812055.865712732813951.671190903811919.146962732813887.869107589
811873.574046075813808.442024261811824.094879359813550.629524246
811864.459462702813301.931607574812088.417796046812492.035774261
812031.126129389812023.285774231811171.751129389812133.962857589
810903.521962702812222.504524276810719.928212732812387.869107589
810407.428212732813132.660774246810192.584462702813442.556607559

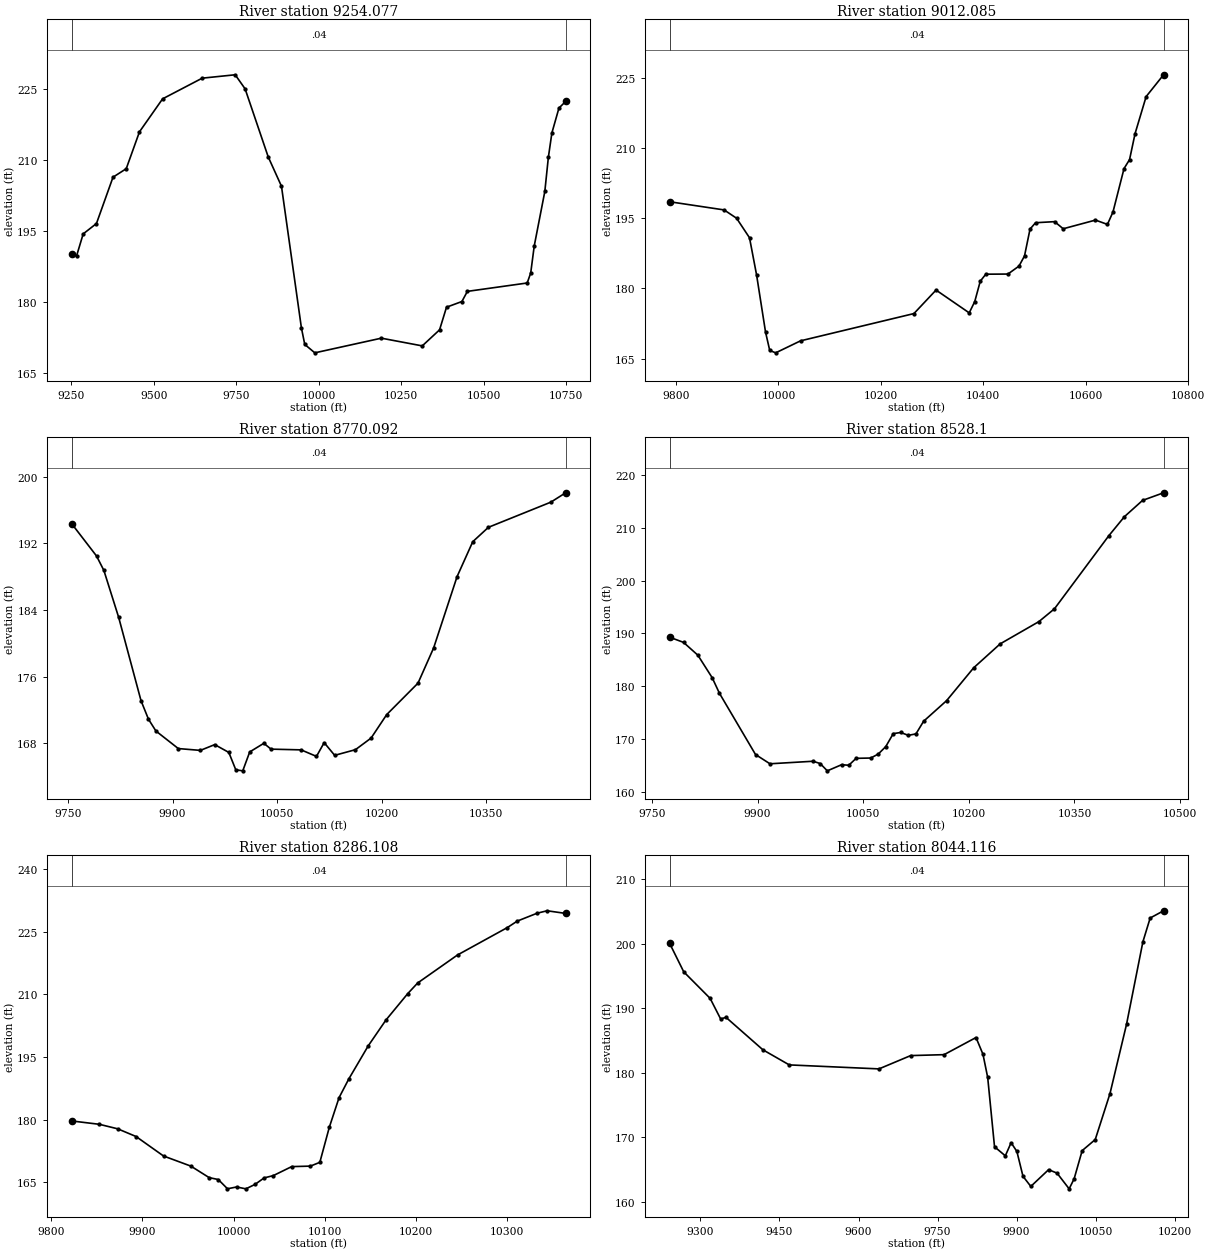
Type RM Length L Ch R = 1 ,9254.077,241.992200,241.992200,241.992200
XS GIS Cut Line= 6
812429.679885478 816333.81135746811816.513723074816294.184127649
811638.590526356816267.154008873811567.657510227816265.890209731
811359.700083914816312.360499484810965.917166943816455.368906168
#Sta/Elev= 30
9250.861190.10999265.629189.72119285.749194.3998 9325.99196.58889376.204206.3909
9416.332208.18299456.461215.98489526.615222.95589646.727227.32789746.821228.0446
9776.849225.06929846.966210.67419887.134204.48559947.587174.53679957.761171.0309
9988.281  169.2510190.09172.351310314.12170.719610366.61 174.11210387.67 178.898
10434.31180.099610450.98182.247310632.35184.017810643.05186.124210653.75191.8472
10685.86203.368310696.57210.576510707.27215.741910728.68221.0031 10749.1222.4139
#Mann= 3 , 0 , 0
9250.861    0.04       09250.861    0.04       0 10749.1    0.04       0
#XS Ineff= 2 , 0
       0                 10078.2       0
Bank Sta=9250.861,10749.1
Exp/Cntr=0.3,0.1

Type RM Length L Ch R = 1 ,9012.085,241.992200,241.992200,241.992200
XS GIS Cut Line= 6
811810.205249818 815937.82033269811697.299117524815996.686770619
 811658.66725627 816033.16540041811612.899834818816100.119572737
811537.751299141816150.666581167810973.491828352816384.981405928
#Sta/Elev= 30
9787.561198.52989894.013196.78279918.358195.00829943.604190.83629957.462182.8699
9974.898170.68339983.088166.76219994.703166.250210043.26168.815310264.53174.6376
10307.73179.661210372.48174.789810383.27177.199310394.07181.557510404.86183.0534
10448.03183.081310469.61 184.77810480.41186.9477 10491.2192.688310501.99194.0476
 10539.2 194.27710555.95192.755310618.96 194.61110642.29193.688310653.09196.3335
10674.67 205.61510685.46207.532910696.26213.101310717.84220.995610751.85 225.654
#Mann= 3 , 0 , 0
9787.561    0.04       09787.561    0.04       010751.85    0.04       0
#XS Ineff= 2 , 0
       0                               0
Bank Sta=9787.561,10751.85
Exp/Cntr=0.3,0.1

Type RM Length L Ch R = 1 ,8770.092,241.992100,241.992100,241.992100
XS GIS Cut Line= 6
811748.859650486 815793.47774606811565.271246638815858.982628122
 811539.54642046815863.565666094811500.527262507815862.600191842
811447.676708748 815878.14723704811095.881760387 816055.34695731
#Sta/Elev= 30
9755.042194.35199790.756190.47419801.303188.73889822.536183.10799854.642173.1049
9865.344170.88539876.046169.46979908.152167.36689939.834167.14739960.459167.8399
9980.703166.90349990.704164.816510000.71164.693210010.72166.962810030.98167.9972
10041.31167.296910084.49167.210710106.57166.425910117.62168.077410132.71166.5534
10162.54167.2328   10185168.625210207.46171.446710252.38175.217510274.84179.4469
 10308.5188.0054   10331192.190210353.46193.918610443.17 196.93910464.43198.0631
#Mann= 3 , 0 , 0
9755.042    0.04       09755.042    0.04       010464.43    0.04       0
#XS Ineff= 2 , 0
       0                   10073       0
Bank Sta=9755.042,10464.43
Exp/Cntr=0.3,0.1

Type RM Length L Ch R = 1 ,  8528.1,241.992200,241.992200,241.992200
XS GIS Cut Line= 6
811654.465019488815601.762304976811475.073253477 815639.95940428
811408.262949577815650.613397638811375.550268311815659.870578709
811192.839915122815734.970054833810994.750057039815827.800624838
#Sta/Elev= 30
9775.056189.2989 9794.87188.30969815.227185.87759835.623181.59219845.868178.6506
9897.093167.02899917.583165.2675 9978.81 165.7499988.933165.31429999.056163.9288
10019.32165.091910029.54164.988410039.93166.302510060.73166.360110071.38167.1146
10082.03168.527610092.69170.992710103.34171.207610114.04 170.66610124.91170.9414
10135.79173.341110168.41 177.24910206.87183.485210244.52188.028510299.51192.2531
10321.59194.683710398.86208.568310420.94212.167910446.67215.2556 10476.5216.7023
#Mann= 3 , 0 , 0
9775.056    0.04       09775.056    0.04       0 10476.5    0.04       0
#XS Ineff= 2 , 0
       0                               0
Bank Sta=9775.056,10476.5
Exp/Cntr=0.3,0.1

Type RM Length L Ch R = 1 ,8286.108,241.992200,241.992200,241.992200
XS GIS Cut Line= 6
811565.120116796 815419.55349913811442.914454013815431.744812393
811366.700983767815425.718443947811316.135826571815430.760876998
811226.962940607815461.121342416811046.371510795815540.426813397
#Sta/Elev= 30
9822.407179.65999852.733178.8582 9872.87177.77499893.006175.93069923.121171.2635
9953.171168.83039973.178166.07959983.227 165.6179993.297163.405310003.38163.8332
10013.44163.387710023.49164.4467 10033.5166.0109 10043.5166.553510063.71168.7152
10084.23168.834110094.59169.739910104.99178.142210115.67185.239410126.36189.7263
10147.73  197.68   10167203.819610190.99210.173510201.91 212.732 10245.6219.4419
 10300.2226.004510311.13 227.56310332.97229.457810343.89230.037610364.24229.4069
#Mann= 3 , 0 , 0
9822.407    0.04       09822.407    0.04       010364.24    0.04       0
#XS Ineff= 2 , 0
       0                               0
Bank Sta=9822.407,10364.24
Exp/Cntr=0.3,0.1

Type RM Length L Ch R = 1 ,8044.116,241.992200,241.992200,241.992200
XS GIS Cut Line= 6
811961.850416392815161.437023595811499.610833049815135.395356938
811312.351793855815202.617295712811277.005719244815224.509366885
811174.705469906815303.642900437811081.982921094815351.615701765
#Sta/Elev= 30
9241.352200.10889268.245195.67479318.325191.56189338.356188.35879348.372188.6234
9418.483183.58859468.562181.24629638.832180.62749698.927182.68929762.416182.8346
 9822.98185.48959836.223182.89329845.182179.2943 9858.14168.55519878.637167.1509
9889.617169.18539900.598167.82599912.153163.98029927.022162.40819960.793165.0065
9976.848164.46579999.769162.033410009.25163.5914 10024.5167.956610049.32169.6752
10077.26176.791210108.64187.519810139.77200.334710153.57204.018410178.98205.1389
#Mann= 3 , 0 , 0
9241.352    0.04       09241.352    0.04       010178.98    0.04       0
#XS Ineff= 2 , 0
       0                               0
Bank Sta=9241.352,10178.98
Exp/Cntr=0.3,0.1

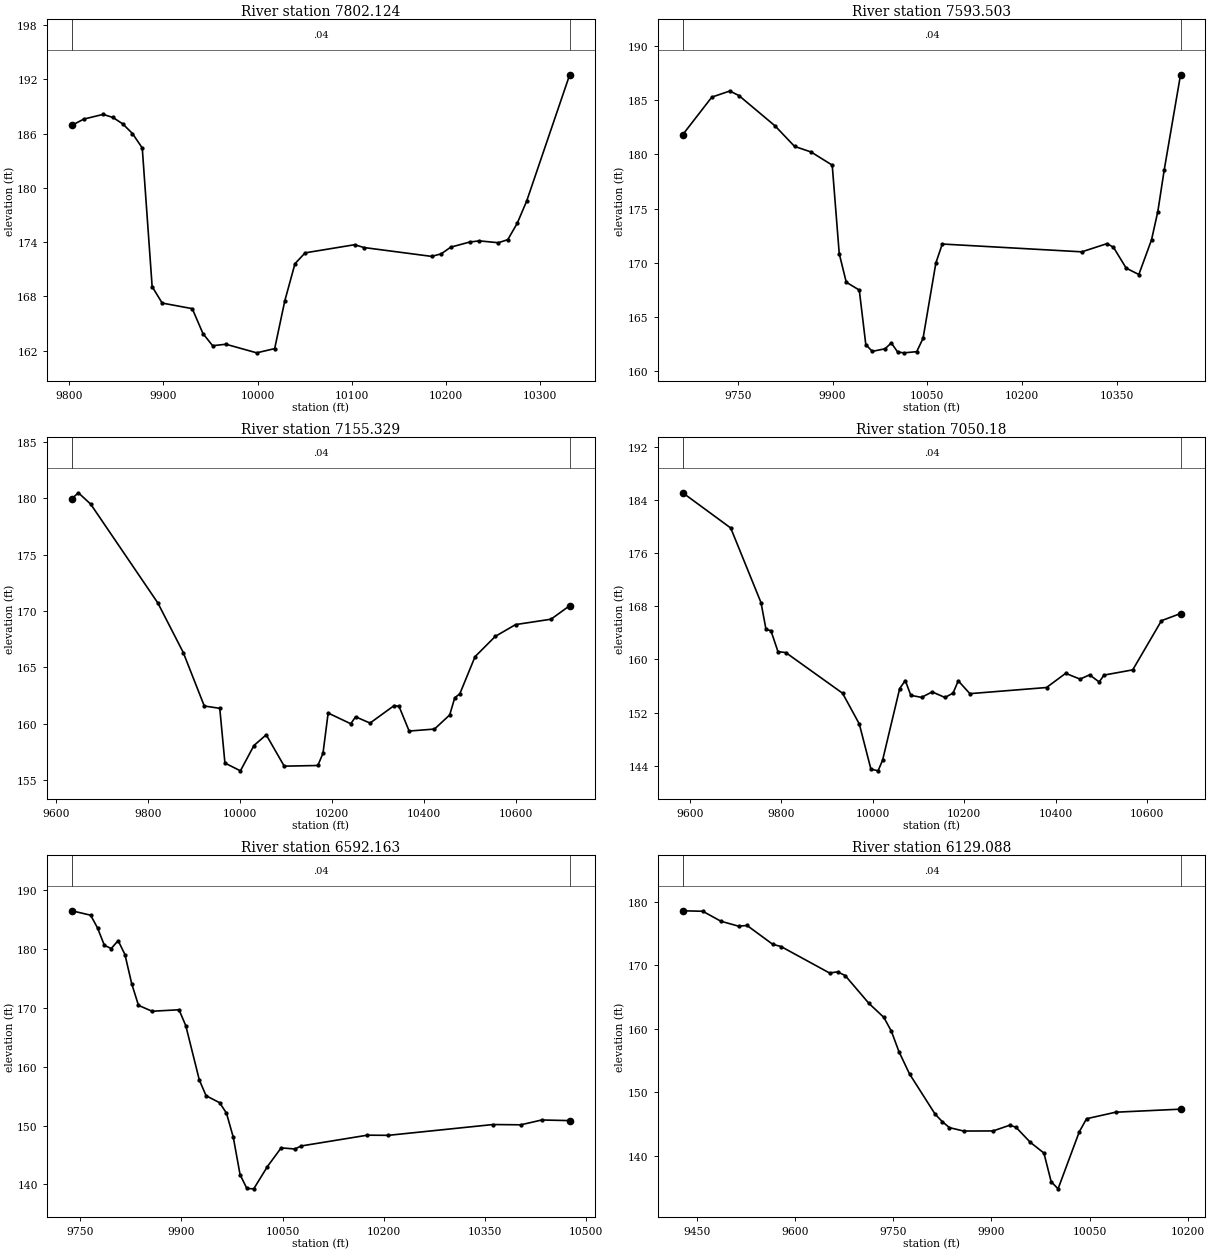
Type RM Length L Ch R = 1 ,7802.124,208.620100,208.620100,208.620100
XS GIS Cut Line= 6
811437.359598183815095.412659446811359.340908792815075.270460197
811201.646873018815010.388526764811157.957989552 814996.64246413
811063.120961636814976.306228422810929.514837634814961.581069633
#Sta/Elev= 30
9802.797186.9095 9815.46187.59839836.029188.11989846.403187.77429856.778187.0705
9867.152 185.9999877.526184.40219888.018169.07669898.665167.25789930.605 166.639
    9942163.87659952.269162.54149966.331162.7058    9999161.7546 10018.1162.2222
10028.89167.520610039.65171.6087 10050.4172.807610102.85173.706210113.13 173.394
10184.76172.417210194.93172.702610205.04173.438610225.24174.007610235.34 174.134
10255.53173.928110265.56174.2671 10275.6176.074410285.64178.5381 10331.3192.4973
#Mann= 3 , 0 , 0
9802.797    0.04       09802.797    0.04       0 10331.3    0.04       0
#XS Ineff= 2 , 0
       0                10086.93       0
Bank Sta=9802.797,10331.3
Exp/Cntr=0.3,0.1

Type RM Length L Ch R = 1 ,7593.503,438.174000,438.174000,438.174000
XS GIS Cut Line= 6
811587.236656398815018.207856938 811442.90350008814874.553608909
811394.756135166814847.603357419811357.636718899814838.401031181
811219.829899877814821.056183621 810869.17789793 814845.55282101
#Sta/Elev= 30
9662.862181.80629708.921185.26729737.359185.83069751.784185.41319808.934182.6229
9839.903180.72739865.913 180.2189899.469179.00149910.569170.85239921.669168.2207
9942.294167.49579952.597162.47829962.835161.84889982.949162.08649993.006162.6257
10003.05161.783910013.09161.714310033.18161.821910043.22163.0529 10063.5169.9955
10073.64171.737310294.46171.018210334.56171.777610344.58171.433110364.63169.5191
10384.68168.928410404.73 172.11510414.75174.728610424.78178.539710450.66187.3263
#Mann= 3 , 0 , 0
9662.862    0.04       09662.862    0.04       010450.66    0.04       0
#XS Ineff= 2 , 0
       0                10109.96       0
Bank Sta=9662.862,10450.66
Exp/Cntr=0.3,0.1

Type RM Length L Ch R = 1 ,7155.329,105.149400,105.149400,105.149400
XS GIS Cut Line= 5
 811815.55708611814970.485565335811712.489317447814878.636057213
811521.160463959814504.325038359 811375.65492782814550.762975439
811038.205918521814707.620007277
#Sta/Elev= 30
9633.894179.96679648.035 180.4879674.824179.48069820.956170.7156 9876.29166.3191
9922.032161.57579955.724161.37119966.954156.516910000.65155.825310030.09158.0699
 10056.8159.0215   10096156.239810169.11156.299910180.34157.379510191.57 160.951
10240.78160.000410251.28160.618510282.77160.061610335.25161.616110345.78161.5445
10367.84159.354210422.98159.530610456.06160.781510467.09162.305210478.11162.6575
 10511.2165.949110555.31167.751110599.42168.796210676.61169.274910717.18170.4723
#Mann= 3 , 0 , 0
9633.894    0.04       09633.894    0.04       010717.18    0.04       0
#XS Ineff= 2 , 0
       0                10094.17       0
Bank Sta=9633.894,10717.18
Exp/Cntr=0.3,0.1

Type RM Length L Ch R = 1 , 7050.18,458.017300,458.017300,458.017300
XS GIS Cut Line= 6
811881.714129806814980.117632926811854.878937364814929.741426319
811746.211659402814687.343002096811642.805380195814545.441293523
811582.473285258814439.646324366 811135.20960924814579.657691821
#Sta/Elev= 30
9584.315185.04489689.319179.75349755.668168.52449766.497164.51799777.326164.3064
9792.734161.16549809.813161.01919933.946154.91779970.618150.29269996.008143.5101
10011.69143.243410021.61144.846310058.97155.6111 10071.2156.8214 10083.4154.5914
10106.79154.285610130.01155.112810158.16154.271210175.72154.932510187.15156.7759
10212.53154.847610380.18155.7681 10422.1157.901610453.53157.032810474.49157.6738
10495.45156.599810505.93157.6365 10568.8158.423410631.67165.816310673.36166.8911
#Mann= 3 , 0 , 0
9584.315    0.04       09584.315    0.04       010673.36    0.04       0
#XS Ineff= 2 , 0
       09909.897        10071.23       0
Bank Sta=9584.315,10673.36
Exp/Cntr=0.3,0.1

Type RM Length L Ch R = 1 ,6592.163,463.074600,463.074600,463.074600
XS GIS Cut Line= 6
812100.458357096814862.020929754812085.767562836814793.396972463
812079.977895826814698.760450244812100.239288062814548.065826371
812096.839125574814449.919808179 811785.00000003 814367.52451241
#Sta/Elev= 30
9737.613186.50799765.439185.75579775.629183.60089785.818180.63189796.008180.0951
9806.198181.44159816.268179.07459826.315174.11939836.363170.43269856.458169.4315
9896.491169.6803  9906.5166.97589926.543 157.7589936.565155.0737 9956.69153.8772
9966.797152.11589976.904148.01919987.011141.64029997.119139.299910007.26 139.241
10027.58143.035810047.89146.206310068.01 146.01810078.02146.536810175.73148.3636
10206.76 148.33610361.91150.172210403.28150.125410434.31150.946610475.68150.8386
#Mann= 3 , 0 , 0
9737.613    0.04       09737.613    0.04       010475.68    0.04       0
#XS Ineff= 2 , 0
       0                10074.71       0
Bank Sta=9737.613,10475.68
Exp/Cntr=0.3,0.1

Type RM Length L Ch R = 1 ,6129.088,285.814100,285.814100,285.814100
XS GIS Cut Line= 6
812671.635304619 814777.12351236812583.660776855814680.099130469
812500.041693919814563.550098929812389.438931817814358.102618053
812348.082895504814329.452898024812162.192288188814255.620493939
#Sta/Elev= 30
9428.683178.6036 9459.31178.52789486.997176.95759513.907176.17979527.031176.2838
9566.175173.31829578.852172.96859652.967168.79279665.089168.98029676.752168.4001
9713.012164.0116 9735.93161.79019747.389159.60759758.848 156.4159775.078152.8837
9814.151146.55019825.085145.36889835.972144.42779857.793143.88759902.611143.9035
9928.231144.8097 9937.65144.48249959.269142.12939980.263140.41949991.342 135.907
10001.89134.778810034.32143.781410045.42145.827210089.84146.856410188.88147.3367
#Mann= 3 , 0 , 0
9428.683    0.04       09428.683    0.04       010188.88    0.04       0
#XS Ineff= 2 , 0
       09913.598        10044.72       0
Bank Sta=9428.683,10188.88
Exp/Cntr=0.3,0.1

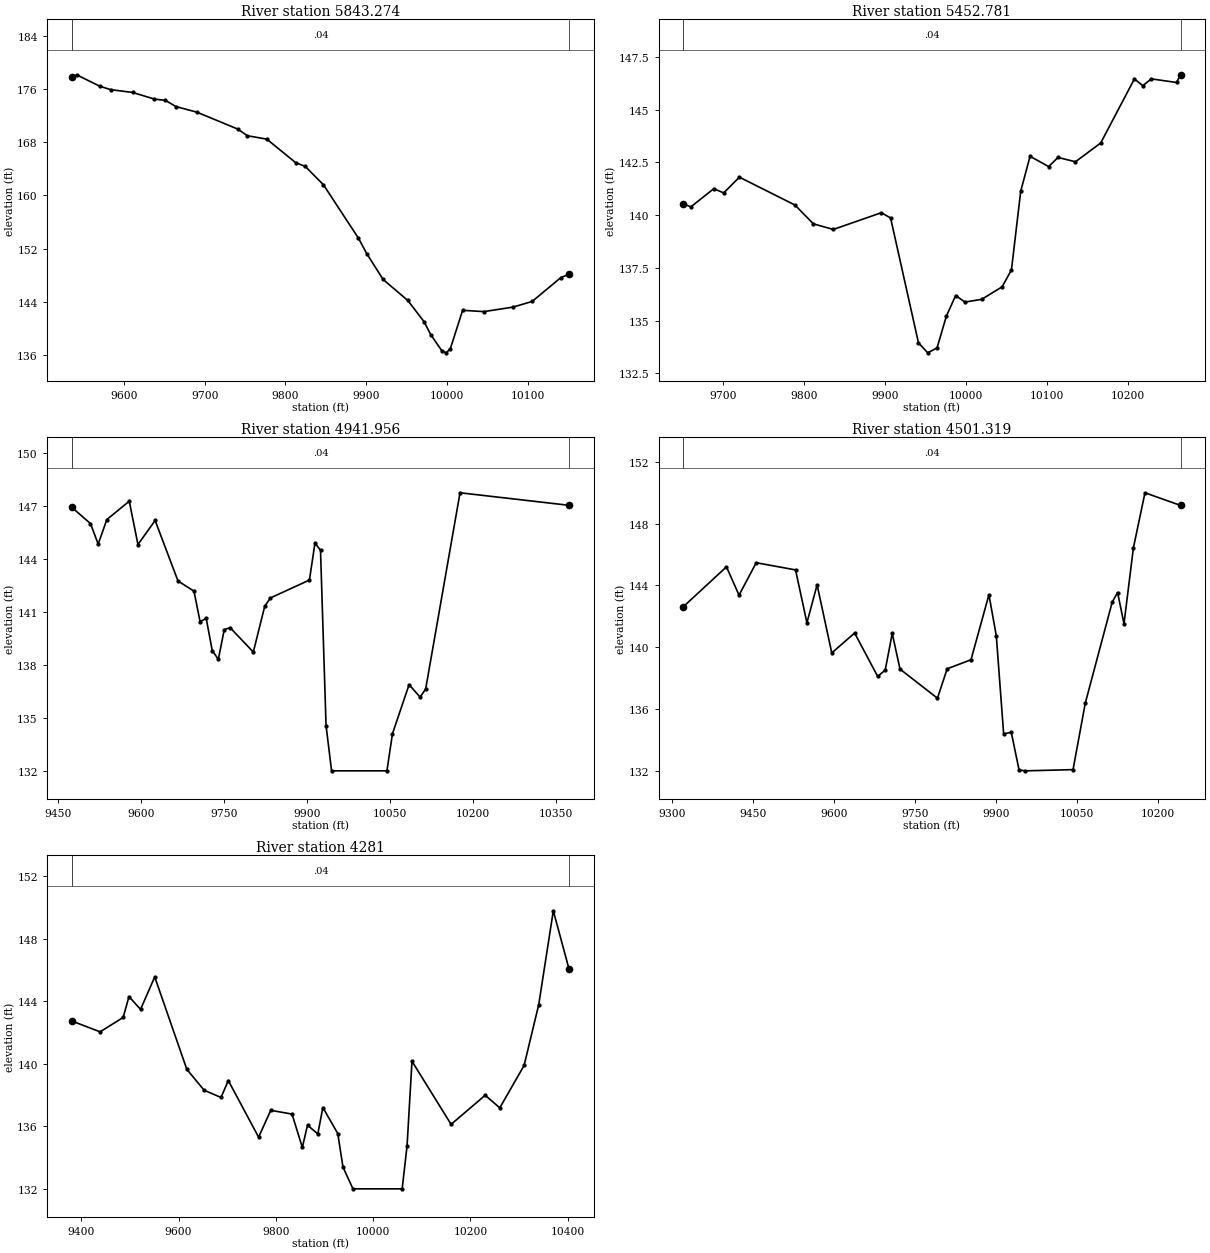
Type RM Length L Ch R = 1 ,5843.274,390.492900,390.492900,390.492900
XS GIS Cut Line= 6
812699.251146585814759.081162304812563.025786936814604.273616165
812500.833458692814502.124135509812490.913699955814411.699476793
812551.414203316814345.282446519812494.293233991814256.656040713
#Sta/Elev= 30
9535.275177.90239541.175178.17059569.881176.44989583.445  175.939610.571175.5103
9637.698174.50889651.261174.31089664.284173.38329690.219172.54039740.808169.9986
9752.843168.98829776.802168.48249812.739164.9277 9824.42164.37769846.961161.6224
 9890.47 153.5579900.713151.23249921.017147.34119951.613144.18029971.838140.9688
 9980.09139.01569994.126136.54829999.388136.295510004.36136.945810019.53142.7013
10045.86142.503910081.89143.179810105.68144.036110141.37147.6398 10151.3148.1234
#Mann= 3 , 0 , 0
9535.275    0.04       09535.275    0.04       0 10151.3    0.04       0
#XS Ineff= 2 , 0
       0                               0
Bank Sta=9535.275,10151.3
Exp/Cntr=0.3,0.1

Type RM Length L Ch R = 1 ,5452.781,510.825500,510.825500,510.825500
XS GIS Cut Line= 6
813031.333285088813949.986778271813007.257916838813974.937614456
812863.553241909814077.971154988812657.653301331814194.117607667
812638.573124799 814205.13372144812500.224441054814244.722806125
#Sta/Elev= 30
9650.904140.54299660.025140.39559688.355141.25719700.659141.05839720.007141.8045
9788.654140.48269811.402139.58939836.011 139.3279895.184140.11769906.665139.8735
9941.109133.9526 9952.59133.47739964.071133.71299975.553135.21449987.034136.1935
9998.515135.884410019.18136.012610044.44136.608510055.92137.4083 10067.4141.1451
10078.88142.792410101.86142.306310113.41142.739110134.95142.533310166.15143.4257
10207.76146.462210218.16146.139810228.56146.463310259.77146.292810264.73146.6576
#Mann= 3 , 0 , 0
9650.904    0.04       09650.904    0.04       010264.73    0.04       0
#XS Ineff= 2 , 0
       09890.249                       0
Bank Sta=9650.904,10264.73
Exp/Cntr=0.3,0.1

Type RM Length L Ch R = 1 ,4941.956,440.637100,440.637100,440.637100
XS GIS Cut Line= 6
812515.012761561813500.875426537 812402.92916676813635.768798167
 812344.46399258813766.550272709812324.883649403813905.709087325
812323.756352054814123.844285681812119.682389387814201.572194023
#Sta/Elev= 30
9475.297146.92079508.998146.00149522.967144.84099538.625 146.2329579.142147.2695
9594.851144.81339625.896146.1784 9667.24142.74849696.143142.17129707.251140.4364
9718.242140.63039729.233138.79499740.224  138.319750.831139.98839761.407140.1043
9803.459138.72189824.012141.31069834.289141.78539904.906142.80139914.923144.8997
 9924.94144.48519934.957134.55189944.958131.987910045.01131.987910055.03134.0904
10085.08136.8734 10105.1136.1636 10115.1136.6314 10177.2147.747510374.18147.0377
#Mann= 3 , 0 , 0
9475.297    0.04       09475.297    0.04       010374.18    0.04       0
#XS Ineff= 2 , 0
       0                               0
Bank Sta=9475.297,10374.18
Exp/Cntr=0.3,0.1

Type RM Length L Ch R = 1 ,4501.319,220.318600,220.318600,220.318600
XS GIS Cut Line= 6
812409.656817958813414.468393621 812329.37053415813472.504332502
812207.197646584813574.290646167811927.899875669813859.451580204
811796.972299333813945.802152561811699.099489008813988.552257356
#Sta/Elev= 30
9320.801142.63069400.582145.20979423.844143.3741 9455.71145.4754  9528.6145.0103
9549.691141.58149568.533144.04459595.729139.62999638.079140.91929680.875 138.104
9694.808138.52369707.822140.88959722.183138.58299791.567136.69339809.617138.6021
 9853.75139.18619887.009 143.4019900.644140.74619914.279134.3835 9928.39134.4879
9942.855132.04149954.557131.987910042.89 132.06610065.52136.368310115.47142.9203
10125.45143.5451 10137.3141.520110154.76146.440910176.18150.008710242.15 149.189
#Mann= 3 , 0 , 0
9320.801    0.04       09320.801    0.04       010242.15    0.04       0
#XS Ineff= 2 , 0
       0                               0
Bank Sta=9320.801,10242.15
Exp/Cntr=0.3,0.1

Type RM Length L Ch R = 1 ,    4281,0.000000,0.000000,0.000000
XS GIS Cut Line= 6
812384.390689809813393.746533117 812090.76778343813577.621536474
811947.702170844813640.230680336811845.716396731813664.687764523
811668.169252789813684.905400231811432.836064943813685.885630792
#Sta/Elev= 30
9380.503142.72639438.672142.0334 9486.09142.95669497.978144.29069521.753143.4688
9550.935145.54879616.856139.6385 9652.37138.29949687.221137.83449702.189138.9157
9764.487135.29389789.451137.01199833.168136.77119854.408134.63629865.027136.0642
9886.204135.50029896.591137.19219927.223135.52689937.964133.38029958.404131.9879
10059.65131.987910069.73134.756410079.82 140.152 10160.2136.113910230.31137.9746
10260.32137.168610310.32139.882510340.34143.765610370.37149.779110402.56146.0626
#Mann= 3 , 0 , 0
9380.503    0.04       09380.503    0.04       010402.56    0.04       0
#XS Ineff= 2 , 0
       0                               0
Bank Sta=9380.503,10402.56
Exp/Cntr=0.3,0.1